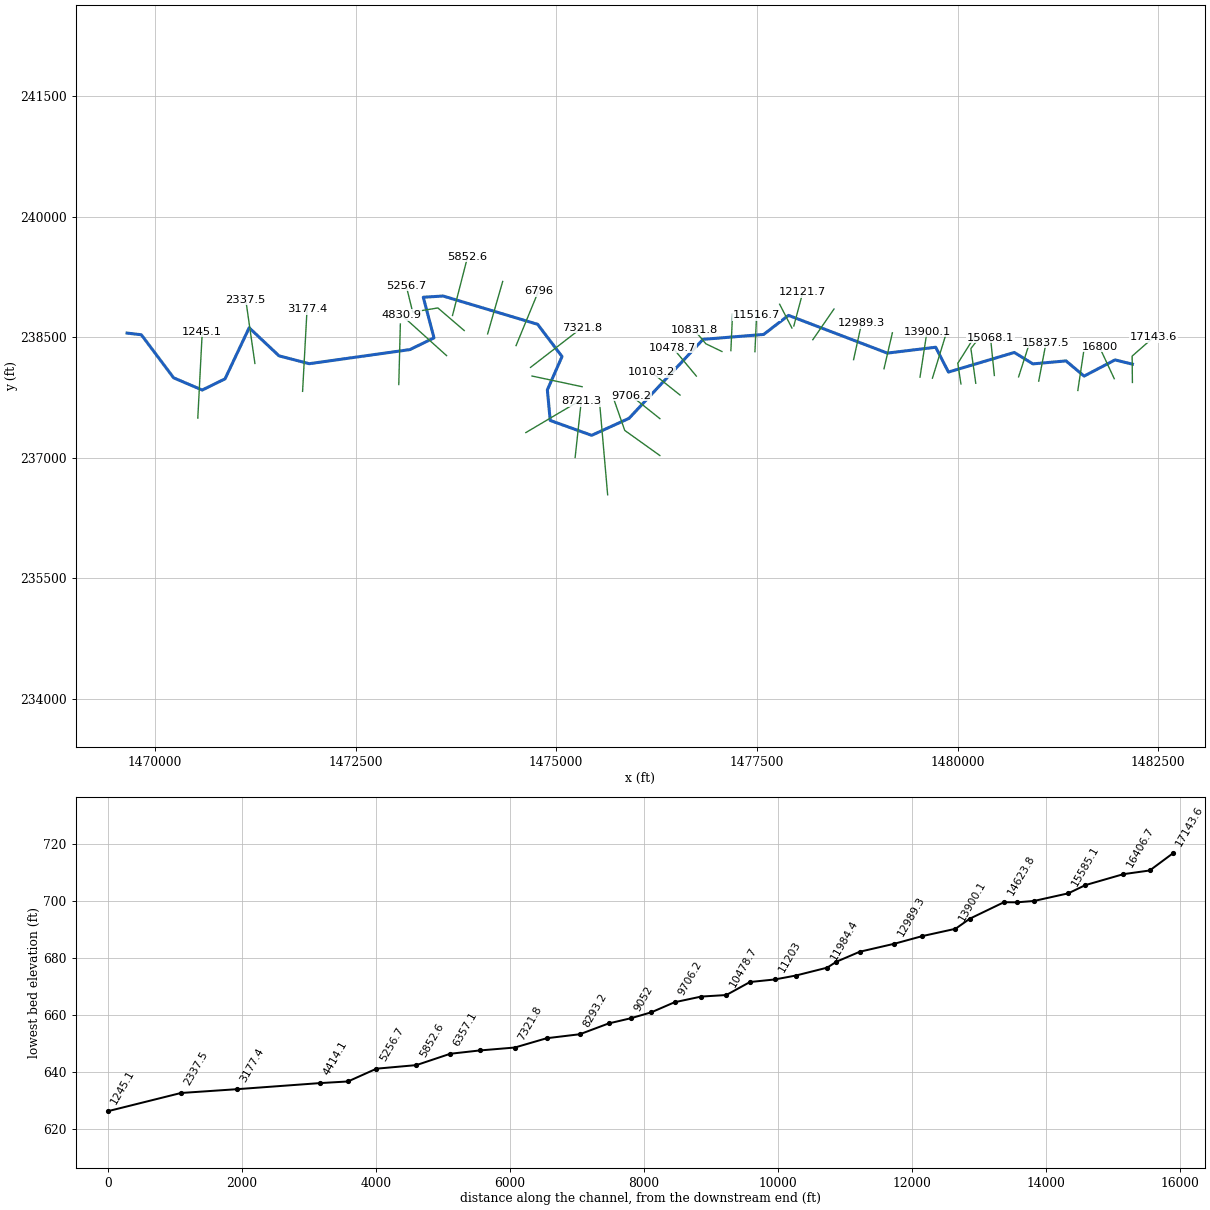
--- GLLSPRN.prj (project) ---

Proj Title=GLLSPRN
Current Plan=p01
Default Exp/Contr=0,0
English Units
Geom File=g01
Flow File=f01
Plan File=p01
BEGIN DESCRIPTION:
END DESCRIPTION:
DSS Export Rating Curves= 0
DSS Export Rating Curve Sorted= 0
DSS Export Volume Flow Curves= 0
DXF OffsetX= 0
DXF OffsetY= 0
DXF ScaleX= 0
DXF ScaleY= 0

--- GLLSPRN.p01 (plan) ---

Plan Title=Floodplain
Program Version=4.00
Geom File=g01
Flow File=f01
K Sum by GR=0
Std Step Tol=0.01
Critical Tol=0.01
Num of Std Step Trials=20
Max Error Tol=0.3
Flow Tol Ratio=0.001
Split Flow NTrial=30
Split Flow Tol=0.02
Split Flow Ratio=0.02
Log Output Level=0
Friction Slope Method=1
Unsteady Friction Slope Method=2
Unsteady Bridges Friction Slope Method=1
Global Log Level=0
CheckData=False
Run HTab=0
Run UNet=0
Run PostProcess=0
UNET Theta=0
UNET Theta Warmup=0
UNET ZTol=0
UNET ZSATol=0
UNET MxIter=0
UNET MaxInSteps=0
UNET DtIC=0
UNET DtMin=0
UNET MaxCRTS=0
UNET WFStab=0
UNET SFStab=0
UNET WFX=0
UNET SFX=0
UNET DSS MLevel=0
UNET DZMax Abort=0
UNET Convert EG Bridges=0
UNET Use Existing IB Tables=0
UNET Froude Limit=0
UNET Froude Power=0
Write IC File=0
Echo Input=False
Echo Output=False
Write Detailed=0

--- GLLSPRN.f01 (steady flow) ---

Flow Title=NFF Regression Equation
Program Version=4.10
Number of Profiles= 1
Profile Names=P100yr
River Rch & RM=GLLSPRN,Main            ,17143.6
876.0936
River Rch & RM=GLLSPRN,Main            ,16406.7
962.5652
River Rch & RM=GLLSPRN,Main            ,13900.1
 1067.63
River Rch & RM=GLLSPRN,Main            ,12469.4
1121.436
River Rch & RM=GLLSPRN,Main            ,8721.3
1225.187
River Rch & RM=GLLSPRN,Main            ,8293.2
1844.301
River Rch & RM=GLLSPRN,Main            ,533.2
  1981.8
River Rch & RM=GLLSPRN,Main            ,249.5
1983.239
Boundary for River Rch & Prof#=GLLSPRN,Main            , 1
Up Type= 0
Dn Type= 3
Dn Slope=0.001
DSS Import GetInterval= 0
DSS Import GetPeak= 0
DSS Import FillOption= 0

--- GLLSPRN.g01 (geometry) ---

Geom Title=USGS 10m DEM
Program Version=4.10

River Reach=GLLSPRN         ,Main
Reach XY= 30
     1482179.261       238162.99     1481962.426      238216.197
     1481577.009      238014.634     1481351.489      238203.696
     1480939.552      238166.475     1480707.202      238308.695
     1479886.689       238064.63     1479728.248      238373.942
     1479125.508      238300.677     1477893.805      238770.538
     1477584.158      238533.128     1476829.163      238471.915
     1475906.798      237488.433     1475441.463      237277.148
     1474925.221      237462.127     1474889.374      237843.222
     1475072.105      238257.617      1474768.72      238659.093
     1473589.739      239011.467     1473343.517      238996.161
      1473477.01       238490.43     1473177.531      238344.596
     1471922.352      238168.791     1471546.107      238266.602
     1471174.232      238616.081     1470873.501      237980.095
     1470589.386      237841.155     1470232.866      237993.064
     1469830.417      238529.291     1469653.328       238549.91

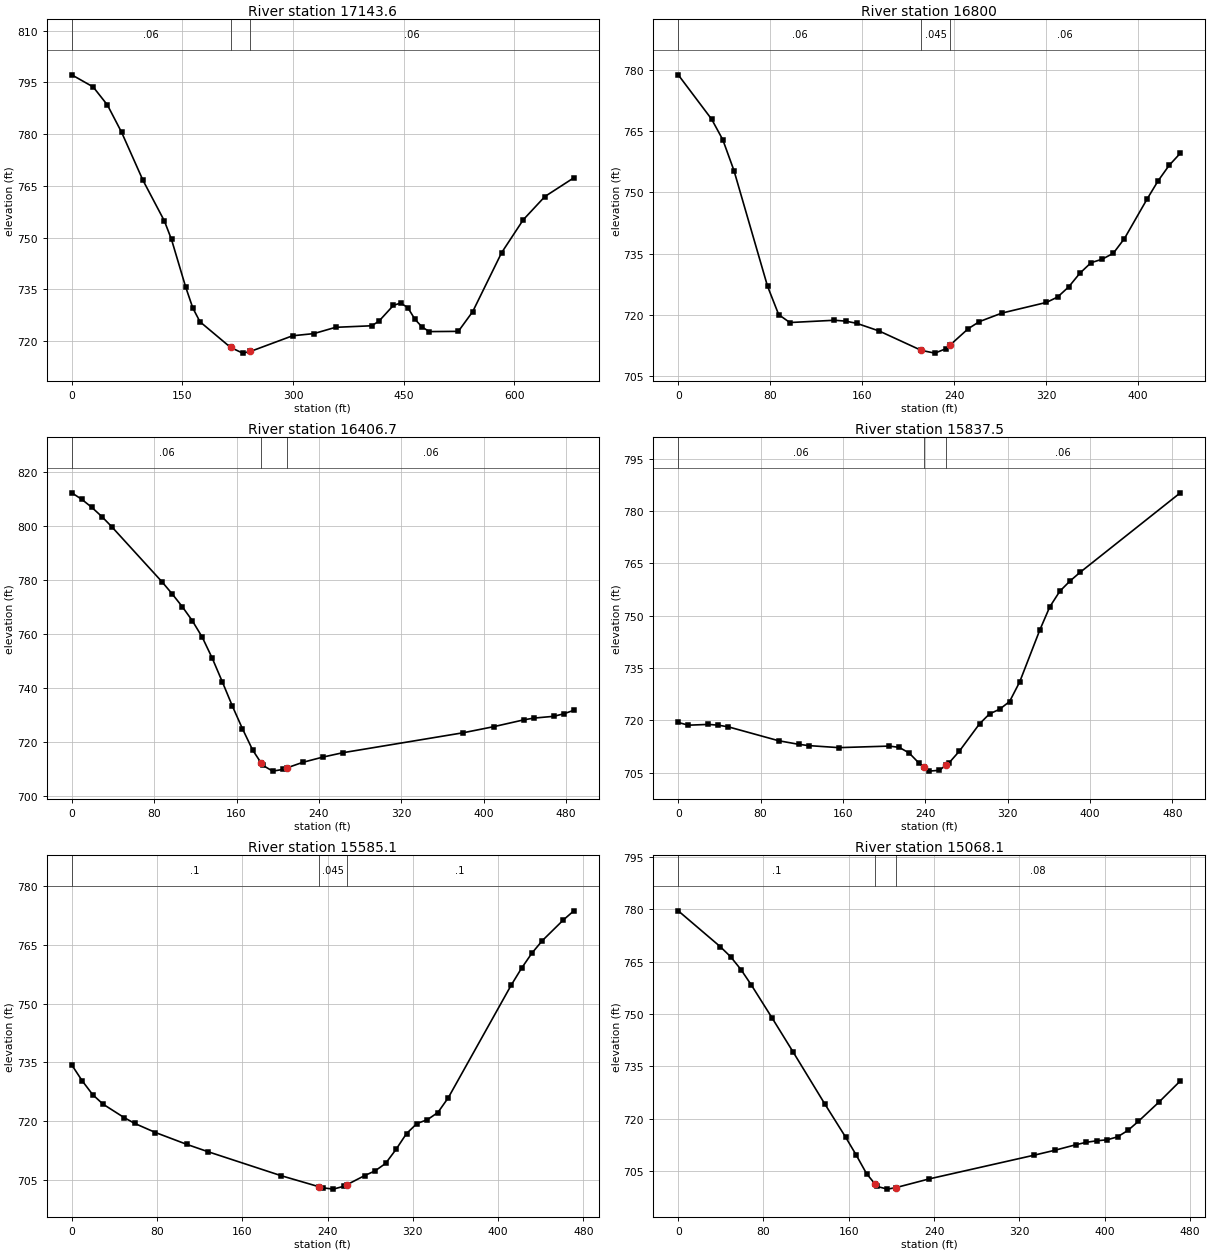
Type RM Length L Ch R = 1 ,17143.6 ,333.9,343.6,352.7
XS GIS Cut Line= 3
     1482178.892      237935.243     1482175.624      238263.444
     1482440.452      238495.828
#Sta/Elev= 30
       0  797.21      29   793.7    48.3  788.47    67.6  780.53    96.5  766.64
   125.5  754.87   135.2  749.48   154.4   735.7   164.1  729.61   173.8  725.63
   215.3718.1906   231.7  716.54   242.2717.0261   299.3  721.57   328.2   722.2
   357.6  724.02   406.5  724.47   416.3  725.78   435.9  730.36   445.7  731.06
   455.4  729.76   465.2  726.35     475  724.08   484.8  722.78     524  722.85
   543.5  728.57   582.7  745.66     612  755.19   641.4  761.94   680.6  767.36
#Mann= 3 , 0 , 0
       0     .06       0   215.3    .045       0   242.2     .06       0
Bank Sta=215.3,242.2
XS Rating Curve= 0 ,0
Exp/Cntr=0.3,0.1

Type RM Length L Ch R = 1 ,16800   ,405.5,393.4,379.1
XS GIS Cut Line= 2
     1481952.535      237982.187     1481767.639       238378.02
#Sta/Elev= 30
       0  778.89    29.1  767.98    38.8  762.94    48.5  755.38    77.7  726.99
    87.4  720.02    97.1  718.07   135.9  718.63   145.6  718.42   155.3  717.88
   174.8     716   211.5711.2368   223.3  710.56     233  711.65   236.5712.5269
   252.4  716.57   262.1   718.3   281.6  720.39   320.4  723.01   330.1  724.33
   339.8  726.83   349.5  730.18   359.2  732.76   368.9  733.62   378.6  735.08
   388.3   738.7   407.8   748.3   417.5  752.83   427.2  756.67   436.9  759.64
#Mann= 3 , 0 , 0
       0     .06       0   211.5    .045       0   236.5     .06       0
Bank Sta=211.5,236.5
XS Rating Curve= 0 ,0
Exp/Cntr=0.3,0.1

Type RM Length L Ch R = 1 ,16406.7 ,568.8,569.1,566.8
XS GIS Cut Line= 2
     1481498.738      237835.637     1481571.686       238317.79
#Sta/Elev= 30
       0  812.28     9.8  809.85    19.5  806.88    29.3  803.46      39  799.66
    87.8  779.27    97.5  774.87   107.3  770.15     117  764.99   126.8  758.78
   136.5     751   146.3  742.24     156  733.32   165.8  724.93   175.6  717.13
     184712.2199   185.3  711.46   195.1  709.27   204.8  709.88   209.1710.4899
   224.3  712.52   243.8  714.46   263.3  716.09   380.4  723.49   409.6  725.71
   438.9  728.24   448.6  728.89   468.1  729.56   477.9   730.5   487.6  731.79
#Mann= 3 , 0 , 0
       0     .06       0     184    .045       0   209.1     .06       0
Bank Sta=184,209.1
XS Rating Curve= 0 ,0
Exp/Cntr=0.3,0.1

Type RM Length L Ch R = 1 ,15837.5 ,255.9,252.4,248.8
XS GIS Cut Line= 2
     1481011.513       237951.71      1481103.16      238430.661
#Sta/Elev= 30
       0  719.38     9.8   718.6    29.3  718.82      39   718.6    48.8  718.11
    97.5  714.14     117  713.11   126.8  712.74     156  712.16   204.8   712.6
   214.6  712.24   224.3  710.61   234.1  707.63   238.9706.5382   243.8  705.42
   253.6  705.66   259.6707.0402   263.3  707.89   273.1  711.18   292.6  718.99
   302.3  721.84   312.1  723.17   321.8  725.39   331.6  731.01   351.1  745.87
   360.8  752.53   370.6  757.04   380.4  759.94   390.1  762.41   487.6  785.26
#Mann= 3 , 0 , 0
       0     .06       0   238.9    .045       0   259.6     .06       0
Bank Sta=238.9,259.6
XS Rating Curve= 0 ,0
Exp/Cntr=0.3,0.1

Type RM Length L Ch R = 1 ,15585.1 ,506.2,517,520.5
XS GIS Cut Line= 2
     1480760.976      238005.562     1480905.575      238453.909
#Sta/Elev= 30
       0  734.32     9.8  730.25    19.6  726.73    29.4  724.28    49.1  720.86
    58.9  719.38    78.5  717.04     108     714   127.6  712.15   196.3  706.01
   231.6703.2025   235.5   702.9   245.4  702.56   255.2  703.29   257.8703.6349
   274.8  706.02   284.6  707.23   294.4  709.12   304.2   712.7   314.1  716.77
   323.9  719.34   333.7  720.32   343.5  722.15   353.3  725.94   412.2  754.67
     422  759.04   431.8  762.93   441.6  766.13   461.3  771.41   471.1  773.73
#Mann= 3 , 0 , 0
       0      .1       0   231.6    .045       0   257.8      .1       0
Bank Sta=231.6,257.8
XS Rating Curve= 0 ,0
Exp/Cntr=0.3,0.1

Type RM Length L Ch R = 1 ,15068.1 ,256.2,257.1,257.9
XS GIS Cut Line= 2
     1480458.753      238022.382     1480411.068      238491.049
#Sta/Elev= 27
       0  779.52    39.3   769.3    49.1   766.4    58.9  762.69    68.7  758.24
    88.3  748.74     108  739.01   137.4   724.3     157  714.77   166.8  709.72
   176.7  704.29   184.5  701.38   186.5  700.63   196.3  699.86   204.5700.3127
   235.5  702.79   333.7  709.56   353.3  710.98   372.9  712.55   382.8  713.26
   392.6  713.69   402.4  713.98   412.2  714.82     422  716.68   431.8  719.27
   451.5   724.9   471.1  730.83
#Mann= 3 , 0 , 0
       0      .1       0   184.5    .045       0   204.5     .08       0
Bank Sta=184.5,204.5
XS Rating Curve= 0 ,0
Exp/Cntr=0.3,0.1

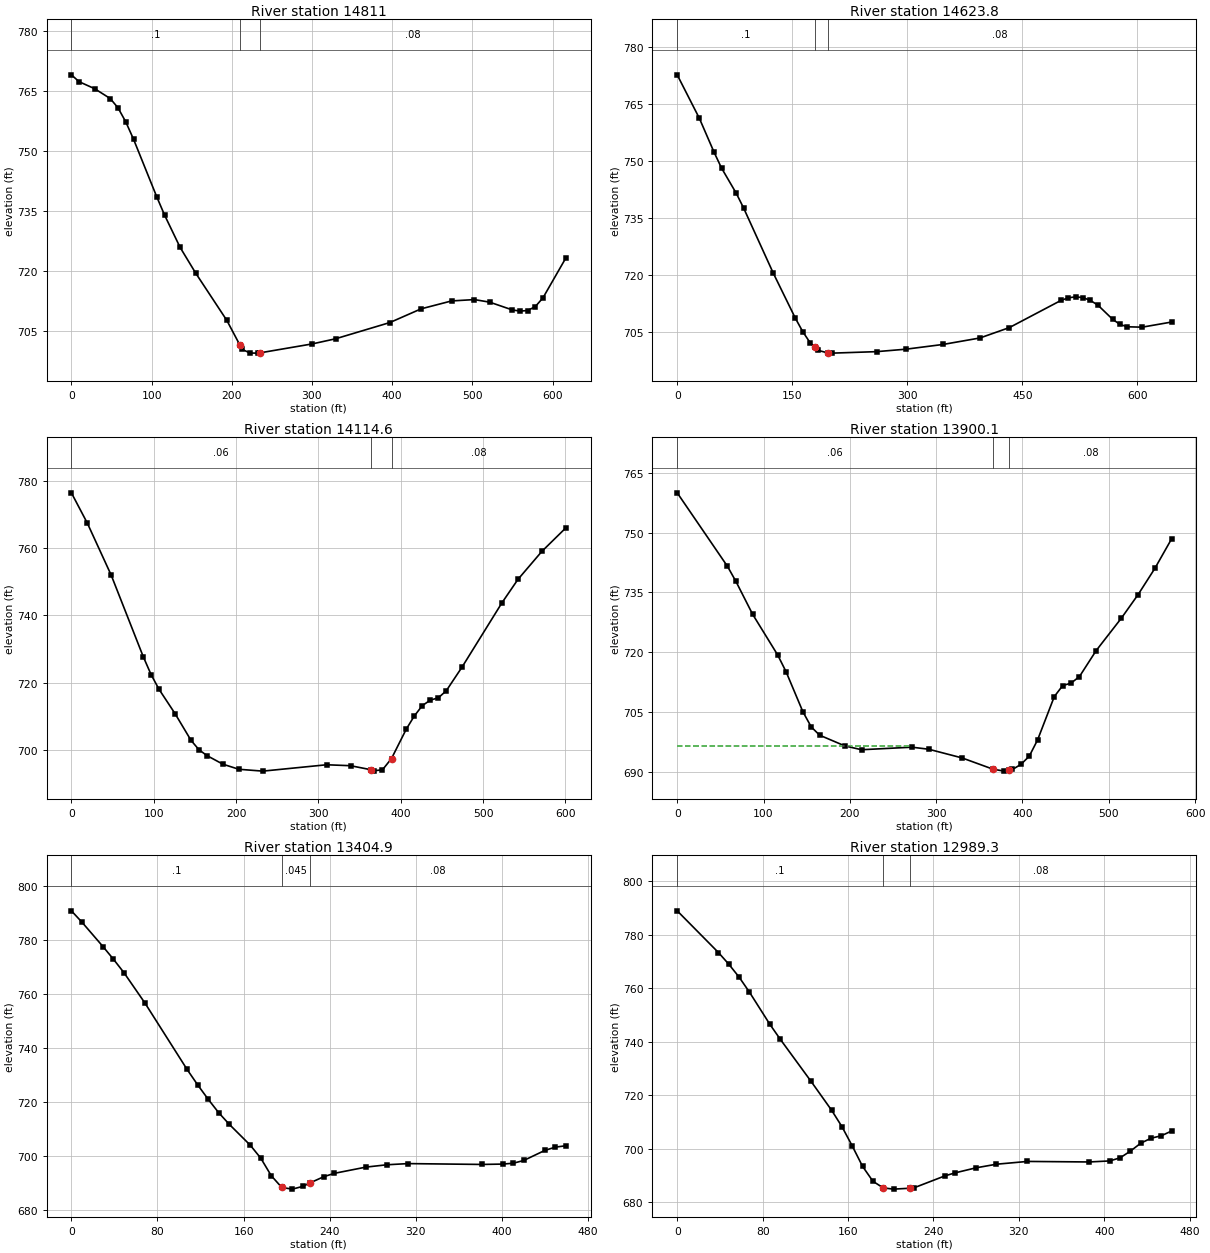
Type RM Length L Ch R = 1 ,14811   ,187,187.2,187.4
XS GIS Cut Line= 3
     1480227.062      237925.341     1480166.504      238357.125
      1480276.32      238500.416
#Sta/Elev= 30
       0  769.05     9.7  767.32    29.1  765.57    48.4  763.12    58.1   760.8
    67.8  757.28    77.5  752.93   106.6  738.44   116.3   733.9   135.6  725.85
     155  719.42   193.8   707.6   209.9701.4937   213.2  700.32   222.8  699.42
   232.5   699.4   234.9699.4594   300.4  701.71   329.4  702.99   397.2  707.06
     436  710.48     474  712.46   502.5   712.8   521.5  712.16     550   710.2
   559.5  709.92     569  710.06   578.5  711.06     588  713.23   616.5   723.2
#Mann= 3 , 0 , 0
       0      .1       0   209.9    .045       0   234.9     .08       0
Bank Sta=209.9,234.9
XS Rating Curve= 0 ,0
Exp/Cntr=0.3,0.1

Type RM Length L Ch R = 1 ,14623.8 ,517.2,509.1,499
XS GIS Cut Line= 3
     1480042.389      237916.689     1480003.326       238173.85
     1480208.405      238499.371
#Sta/Elev= 30
       0  772.56    28.9  761.14    48.2  752.17    57.8  748.07    77.1  741.41
    86.7  737.53   125.2   720.5   154.1  708.61   163.8  705.06   173.4  702.16
   179.3700.9554     183   700.2     197699.4744   202.3  699.44   260.1  699.83
   298.6  700.48   346.7  701.72   394.8  703.42   433.2  706.15   500.6   713.3
   510.2  713.98   519.8  714.23   529.4  714.02     539  713.27   548.7  712.04
   567.9  708.32   577.5  706.97   587.1  706.36   606.4  706.26   644.8  707.61
#Mann= 3 , 0 , 0
       0      .1       0   179.3    .045       0     197     .08       0
Bank Sta=179.3,197
XS Rating Curve= 0 ,0
Exp/Cntr=0.3,0.1

Type RM Length L Ch R = 1 ,14114.6 ,211.1,214.6,217.6
XS GIS Cut Line= 2
     1479687.273      237988.615     1479863.929      238562.569
#Sta/Elev= 30
       0  776.34    19.4  767.32    48.4  751.86    87.2  727.72    96.9   722.3
   106.5  717.96   125.9  710.76   145.3  702.82     155  700.02   164.7  698.29
     184  695.74   203.4  694.23   232.5  693.68     310  695.57     339  695.29
   363.3694.1218   368.1  693.81   377.8  694.07   388.8697.4226   406.8  706.18
   416.5  710.06   426.2  713.14   435.9  714.76   445.6  715.45   455.2  717.51
   474.6  724.63     523   743.7   542.4  750.64   571.5  758.97   600.5  765.92
#Mann= 3 , 0 , 0
       0     .06       0   363.3    .045       0   388.8     .08       0
Bank Sta=363.3,388.8
XS Rating Curve= 0 ,0
Exp/Cntr=0.3,0.1

Type RM Length L Ch R = 1 ,13900.1 ,496.6,495.1,493.3
XS GIS Cut Line= 2
     1479532.492      238001.397     1479619.115      238567.624
#Sta/Elev= 30
       0  759.98    58.2  741.54      68  737.76    87.4  729.49   116.5  719.25
   126.2  715.04   145.6  705.04   155.3  701.22     165  699.15   194.2  696.46
   213.6   695.5   271.8  696.14   291.3  695.63   330.1  693.44   365.6690.6385
   378.6  690.13   384.8 690.392   388.4  690.54   398.1  691.81   407.8  693.85
   417.5  697.96   436.9  708.85   446.6   711.6   456.3  712.22     466  713.86
   485.4  720.39   514.6  728.53     534  734.45   553.4  741.02   572.8  748.44
#Mann= 3 , 0 , 0
       0     .06       0   365.6    .045       0   384.8     .08       0
#XS Ineff= 2 , 0
          271.05  696.38
Permanent Ineff=
       F       F
Bank Sta=365.6,384.8
XS Rating Curve= 0 ,0
Exp/Cntr=0.3,0.1

Type RM Length L Ch R = 1 ,13404.9 ,414.9,415.6,415.3
XS GIS Cut Line= 2
     1479083.884      238105.817     1479188.081      238553.286
#Sta/Elev= 30
       0  790.93     9.8  786.72    29.3  777.68    39.1  772.95    48.9  767.93
    68.4  756.65   107.5  732.02   117.3  726.31   127.1  720.95   136.8  715.99
   146.6  711.68   166.2  703.89     176  699.05   185.7  692.56   195.5  688.18
   205.3  687.57   215.1   688.6   221.5 689.847   234.6   692.2   244.4  693.44
   273.7  695.75   293.3  696.62   312.8  697.05   381.2  696.74   400.8  696.87
   410.6  697.19   420.3  698.21   439.9  701.95   449.7  703.17   459.4  703.67
#Mann= 3 , 0 , 0
       0      .1       0   195.5    .045       0   221.5     .08       0
Bank Sta=195.5,221.5
XS Rating Curve= 0 ,0
Exp/Cntr=0.3,0.1

Type RM Length L Ch R = 1 ,12989.3 ,527.6,519.9,509.4
XS GIS Cut Line= 2
     1478704.652       238218.92     1478804.359       238671.06
#Sta/Elev= 30
       0     789    38.6   773.4    48.2  769.09    57.9  764.24    67.5  758.68
    86.8  746.53    96.5  740.97   125.4  725.18   144.7  714.35   154.3  708.25
     164  700.99   173.6   693.4   183.3  687.84   192.9  685.36   202.6   684.9
   218.2685.2392   221.9  685.42   250.8  689.87   260.4     691   279.7  692.86
     299  694.22     328  695.26   385.8  695.06   405.1  695.45   414.8  696.62
   424.4  699.12   434.1  702.08   443.7  703.94   453.4  704.87     463  706.65
#Mann= 3 , 0 , 0
       0      .1       0   192.9    .045       0   218.2     .08       0
Bank Sta=192.9,218.2
XS Rating Curve= 0 ,0
Exp/Cntr=0.3,0.1

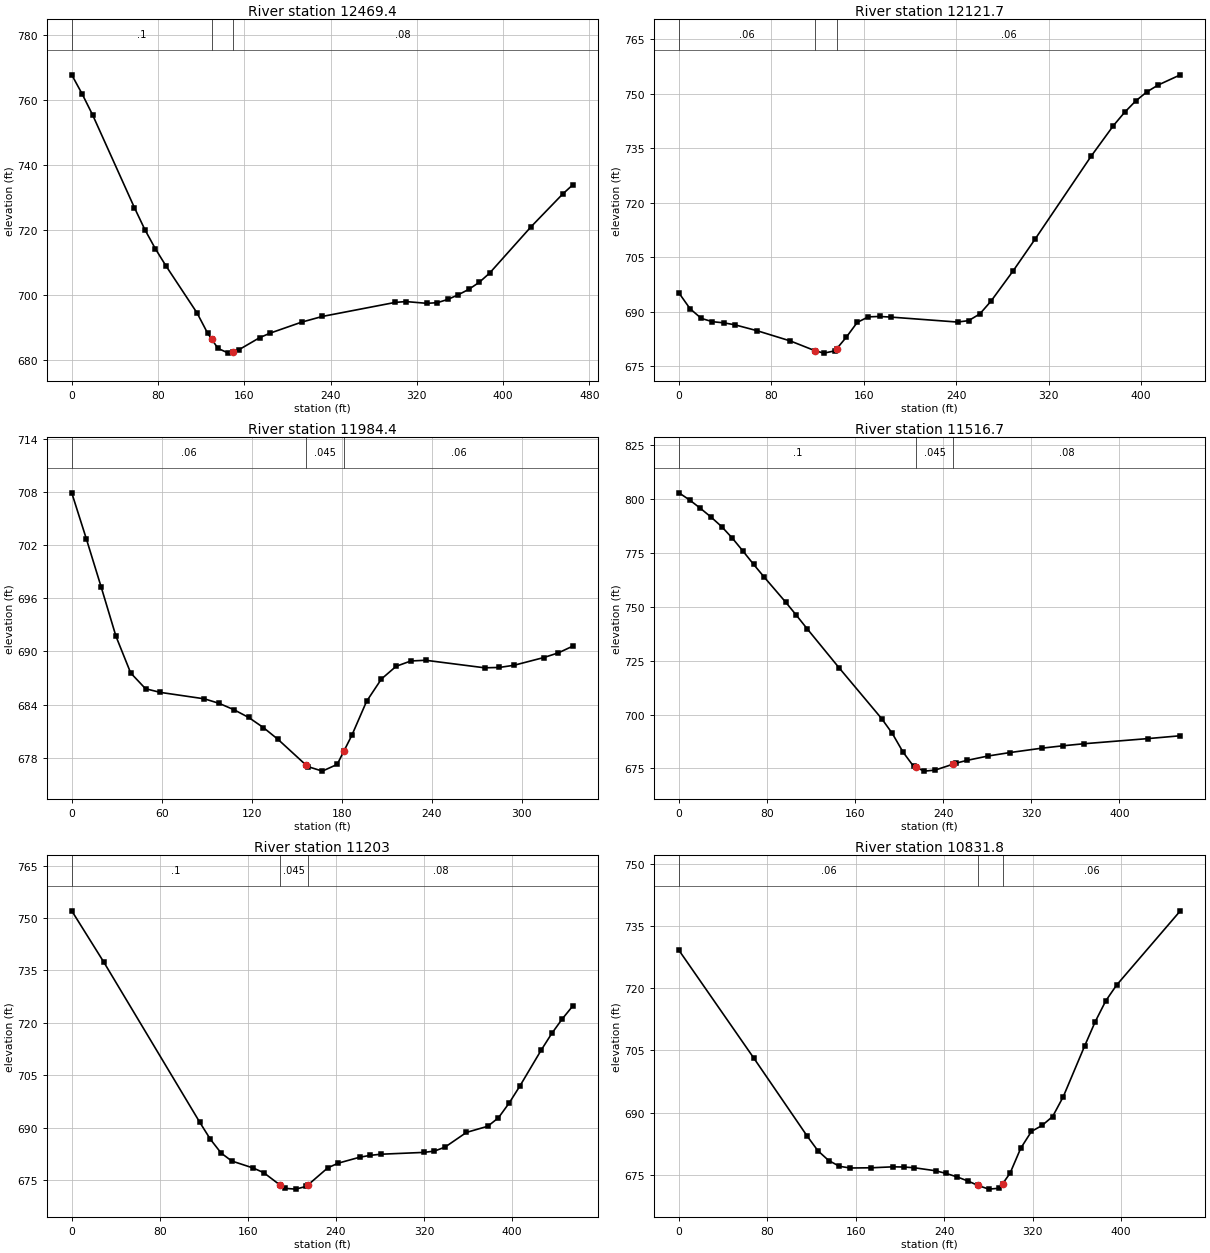
Type RM Length L Ch R = 1 ,12469.4 ,339.2,347.7,354.7
XS GIS Cut Line= 2
     1478196.927      238467.444     1478461.013         238850.
#Sta/Elev= 30
       0  767.64     9.7  761.73    19.4  755.29    58.1  726.82    67.8  720.06
    77.5  714.19    87.2  708.99   116.2  694.43   125.9  688.27   129.8686.3633
   135.6  683.53   145.3  682.08   149.1682.4848     155  683.12   174.3  686.84
     184  688.23   213.1   691.6   232.4  693.36   300.2  697.69   309.9  697.93
   329.3  697.39     339  697.59   348.6  698.58   358.3     700     368  701.66
   377.7  703.81   387.4  706.65   426.1     721   455.2  730.98   464.9  733.91
#Mann= 3 , 0 , 0
       0      .1       0   129.8    .045       0   149.1     .08       0
Bank Sta=129.8,149.1
XS Rating Curve= 0 ,0
Exp/Cntr=0.3,0.1

Type RM Length L Ch R = 1 ,12121.7 ,120.6,137.4,154.1
XS GIS Cut Line= 2
     1477960.348      238638.437     1478072.327      239057.708
#Sta/Elev= 30
       0  695.12     9.6   690.8    19.3  688.14    28.9  687.23    38.6  686.92
    48.2  686.39    67.5  684.76    96.4  681.93   117.8679.2391   125.4  678.58
     135  679.21   136.6679.8169   144.7   682.9   154.3  687.03   163.9  688.56
   173.6  688.67   183.2   688.5   241.1  687.13   250.7  687.52   260.4  689.36
     270  692.84   289.3  701.23   308.6  710.11   356.8  732.78   376.1   741.2
   385.8  744.86   395.4  747.98     405  750.46   414.7  752.34     434  755.16
#Mann= 3 , 0 , 0
       0     .06       0   117.8    .045       0   136.6     .06       0
Bank Sta=117.8,136.6
XS Rating Curve= 0 ,0
Exp/Cntr=0.3,0.1

Type RM Length L Ch R = 1 ,11984.4 ,478.8,467.7,454.6
XS GIS Cut Line= 2
      1477936.91      238612.395     1477783.264       238909.27
#Sta/Elev= 30
       0  707.89     9.8  702.67    19.7  697.23    29.5  691.71    39.3  687.58
    49.2   685.8      59  685.39    88.5  684.66    98.3  684.15   108.2  683.43
     118  682.56   127.8  681.42   137.6  680.08   156.5677.1484   157.3  677.03
   167.1  676.51     177  677.27   181.6678.8143   186.8  680.56   196.6  684.38
   206.5   686.9   216.3  688.33   226.1  688.93     236  689.01   275.3  688.16
   285.1   688.2     295  688.45   314.6  689.31   324.4  689.84   334.3  690.62
#Mann= 3 , 0 , 0
       0     .06       0   156.5    .045       0   181.6     .06       0
Bank Sta=156.5,181.6
XS Rating Curve= 0 ,0
Exp/Cntr=0.3,0.1

Type RM Length L Ch R = 1 ,11516.7 ,313.5,313.7,313.3
XS GIS Cut Line= 2
     1477475.729      238318.088     1477496.185      238773.043
#Sta/Elev= 30
       0  802.86     9.7  799.52    19.4   795.7    29.1  791.62    38.8  787.18
    48.4  781.88    58.1  775.85    67.8  769.66    77.5   763.7    96.9  752.16
   106.6  746.08   116.3  739.87   145.3  721.76   184.1  698.11   193.8  691.21
   203.5  682.59   213.2   675.9   215.2675.4572   222.9  673.75   232.6  674.22
   249.1676.9951   251.9  677.48   261.6  678.74     281  680.79   300.4  682.35
   329.4  684.39   348.8  685.51   368.2  686.47   426.4  688.86   455.4  690.16
#Mann= 3 , 0 , 0
       0      .1       0   215.2    .045       0   249.1     .08       0
Bank Sta=215.2,249.1
XS Rating Curve= 0 ,0
Exp/Cntr=0.3,0.1

Type RM Length L Ch R = 1 ,11203   ,354.2,371.2,388
XS GIS Cut Line= 2
     1477176.031      238331.564     1477196.488      238786.519
#Sta/Elev= 30
       0  752.09    29.1  737.41   116.3  691.52     126  686.63   135.7  682.71
   145.3  680.44   164.7  678.44   174.4  677.09     189673.5995   193.8   672.6
   203.5  672.38   213.2  673.19   214.6 673.584   232.6  678.49   242.2  679.83
   261.6  681.52   271.3  682.06     281  682.38   319.8   682.9   329.4  683.27
   339.1  684.42   358.5  688.62   377.9  690.39   387.6  692.82   397.3  697.03
     407  701.88   426.4  712.19     436  716.96   445.7   721.2   455.4  724.95
#Mann= 3 , 0 , 0
       0      .1       0     189    .045       0   214.6     .08       0
Bank Sta=189,214.6
XS Rating Curve= 0 ,0
Exp/Cntr=0.3,0.1

Type RM Length L Ch R = 1 ,10831.8 ,352.4,353.2,352.4
XS GIS Cut Line= 3
     1477064.514      238320.729     1476863.993      238417.083
     1476715.556      238594.166
#Sta/Elev= 30
       0  729.22    67.7  703.16   116.1  684.25   125.7  680.75   135.4   678.4
   145.1     677   154.8  676.59   174.1  676.64   193.4  676.87   203.1  676.83
   212.8  676.65   232.1  675.92   241.7  675.27   251.4  674.45     261  673.48
   270.6  672.36   280.2  671.48   289.9   671.7   292.7672.7619   299.5  675.34
   309.1  681.35   318.8  685.43   328.4  686.87     338  689.04   347.6  693.83
   366.9  706.07   376.5  711.96   386.1  717.03   395.8   720.8   453.5  738.77
#Mann= 3 , 0 , 0
       0     .06       0   270.6    .045       0   292.7     .06       0
Bank Sta=270.6,292.7
XS Rating Curve= 0 ,0
Exp/Cntr=0.3,0.1

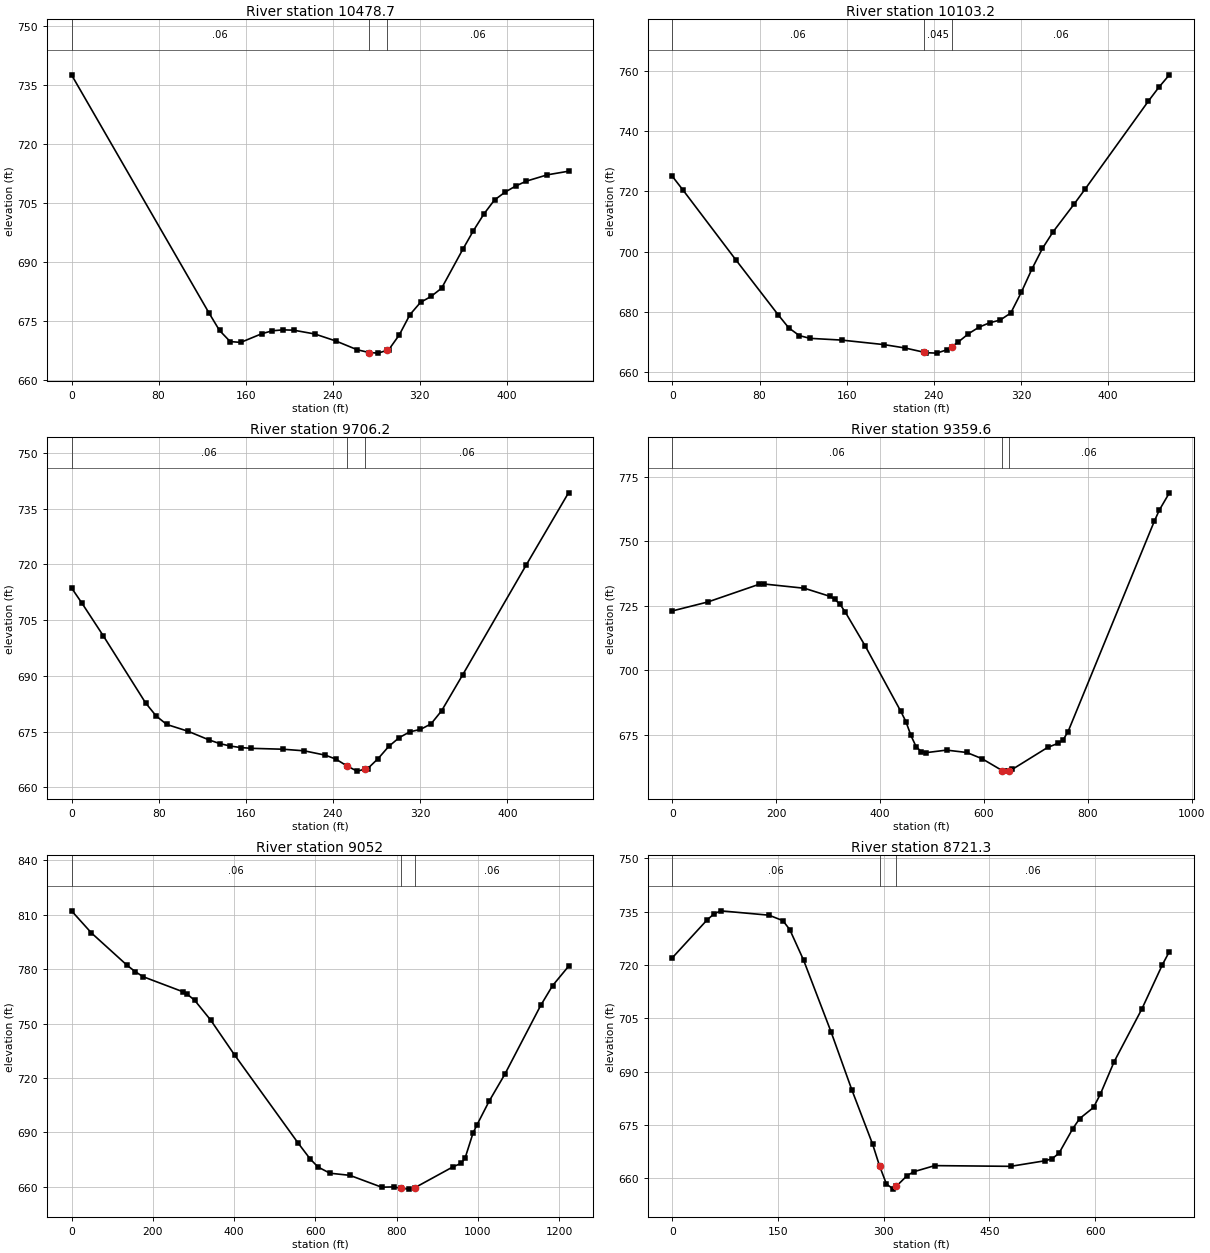
Type RM Length L Ch R = 1 ,10478.7 ,371,375.4,380
XS GIS Cut Line= 2
      1476745.49       238014.94     1476453.066      238365.791
#Sta/Elev= 30
       0  737.51   126.3  677.12     136  672.67   145.8  669.85   155.5  669.64
   174.9  671.85   184.6  672.59   194.4  672.82   204.1  672.74   223.5  671.78
   242.9     670   262.4  667.79   273.3667.0768   281.8  666.92   290.1667.6559
   291.5  667.78   301.2  671.54     311  676.69   320.7  679.79   330.4   681.3
   340.1   683.4   359.6  693.27   369.3  697.97     379  702.23   388.7  705.77
   398.4  707.75   408.2  709.31   417.9  710.54   437.3  712.15   456.7  713.06
#Mann= 3 , 0 , 0
       0     .06       0   273.3    .045       0   290.1     .06       0
Bank Sta=273.3,290.1
XS Rating Curve= 0 ,0
Exp/Cntr=0.3,0.1

Type RM Length L Ch R = 1 ,10103.2 ,396.5,397.1,396
XS GIS Cut Line= 2
     1476542.303      237778.942      1476185.44      238063.183
#Sta/Elev= 30
       0  724.93     9.7  720.43    58.2   697.3    97.1  679.08   106.8  674.76
   116.5  672.19   126.2  671.28   155.3   670.7   194.1  669.21   213.6  668.08
   230.7666.6955     233  666.52   242.7  666.38   252.4  667.54   256.3 668.517
   262.1  669.97   271.8  672.81   281.5  674.99   291.2  676.43   300.9  677.34
   310.6  679.67   320.3  686.56     330  694.23   339.7  701.09   349.4  706.55
   368.9  715.83   378.6  720.61   436.8  749.82   446.5  754.45   456.2  758.59
#Mann= 3 , 0 , 0
       0     .06       0   230.7    .045       0   256.3     .06       0
Bank Sta=230.7,256.3
XS Rating Curve= 0 ,0
Exp/Cntr=0.3,0.1

Type RM Length L Ch R = 1 ,9706.2  ,357.8,346.5,333
XS GIS Cut Line= 2
      1476291.55      237484.959     1475934.687        237769.2
#Sta/Elev= 30
       0  713.67     9.7   709.5    29.1  700.81      68  682.73    77.7  679.22
    87.4  676.94   106.8  675.13   126.2  672.79   135.9  671.81   145.6  671.14
   155.3  670.73     165  670.52   194.1  670.28   213.6  669.85     233  668.68
   242.7  667.62   252.8665.7896   262.1  664.39   269.7664.9071   271.8  665.05
   281.5  667.78   291.2  671.04   300.9  673.42   310.6  674.96   320.3  675.61
     330  677.09   339.7  680.61   359.2  690.36   417.4  719.84   456.2  739.23
#Mann= 3 , 0 , 0
       0     .06       0   252.8    .045       0   269.7     .06       0
Bank Sta=252.8,269.7
XS Rating Curve= 0 ,0
Exp/Cntr=0.3,0.1

Type RM Length L Ch R = 1 ,9359.6  ,311.7,307.6,297.1
XS GIS Cut Line= 3
     1476291.092      237025.986     1475853.592      237338.486
     1475714.703      237734.319
#Sta/Elev= 30
       0     723    68.4  726.48   166.2  733.27     176  733.45   254.2  731.79
     303  728.68   312.8  727.47   322.6   725.6   332.4  722.73   371.5  709.35
   439.9  684.05   449.7  680.07   459.4  674.69   469.2  670.41     479  668.48
   488.8  668.04   527.9  669.02   566.9   668.1   596.2   665.7   635.1661.0878
     645  660.87   648.3661.1076   654.7  661.57     723  670.11   742.5  671.62
   752.3  672.94     762  676.21   927.9   757.7   937.6  762.06   957.1   768.8
#Mann= 3 , 0 , 0
       0     .06       0   635.1    .045       0   648.3     .06       0
Bank Sta=635.1,648.3
XS Rating Curve= 0 ,0
Exp/Cntr=0.3,0.1

Type RM Length L Ch R = 1 ,9052    ,331.6,330.7,330.5
XS GIS Cut Line= 2
     1475640.667      236536.837     1475534.147      237755.153
#Sta/Elev= 30
       0  812.12    48.9  799.95     137  782.06   156.5  778.66   176.1  775.83
   273.9  767.55   283.7   766.4   303.3  762.76   342.4  751.94   401.1  732.76
   557.7  684.14     587  675.48   606.6  670.96   635.9  667.55   684.9  666.38
   763.1  659.85   792.5     660     810659.2889   831.6  658.78   844.6 659.524
   939.2  671.12   958.8     673   968.6  675.95   988.2   689.8   997.9  694.23
  1027.3  707.09  1066.4  722.11  1154.5  759.97  1183.8   770.9    1223  781.53
#Mann= 3 , 0 , 0
       0     .06       0     810    .045       0   844.6     .06       0
Bank Sta=810,844.6
XS Rating Curve= 0 ,0
Exp/Cntr=0.3,0.1

Type RM Length L Ch R = 1 ,8721.3  ,449.1,428.1,406.9
XS GIS Cut Line= 2
     1475235.536      237001.681     1475311.925      237703.069
#Sta/Elev= 30
       0  722.03      49   732.6    58.8  734.31    68.6  735.21   137.2  733.98
   156.8  732.45   166.6  729.94   186.2  721.36   225.4  701.09   254.8  684.84
   284.2  669.61     294  663.52   303.8  658.41   313.6  656.96   317.9657.7629
   333.2  660.76     343  661.87   372.4  663.57   480.2  663.37   529.2  664.94
     539   665.5   548.8  667.06   568.4  673.98   578.2  676.81   597.8  679.92
   607.6  683.71   627.1   692.8   666.3  707.56   695.7  720.11   705.5  723.77
#Mann= 3 , 0 , 0
       0     .06       0     294    .045       0   317.9     .06       0
Bank Sta=294,317.9
XS Rating Curve= 0 ,0
Exp/Cntr=0.3,0.1

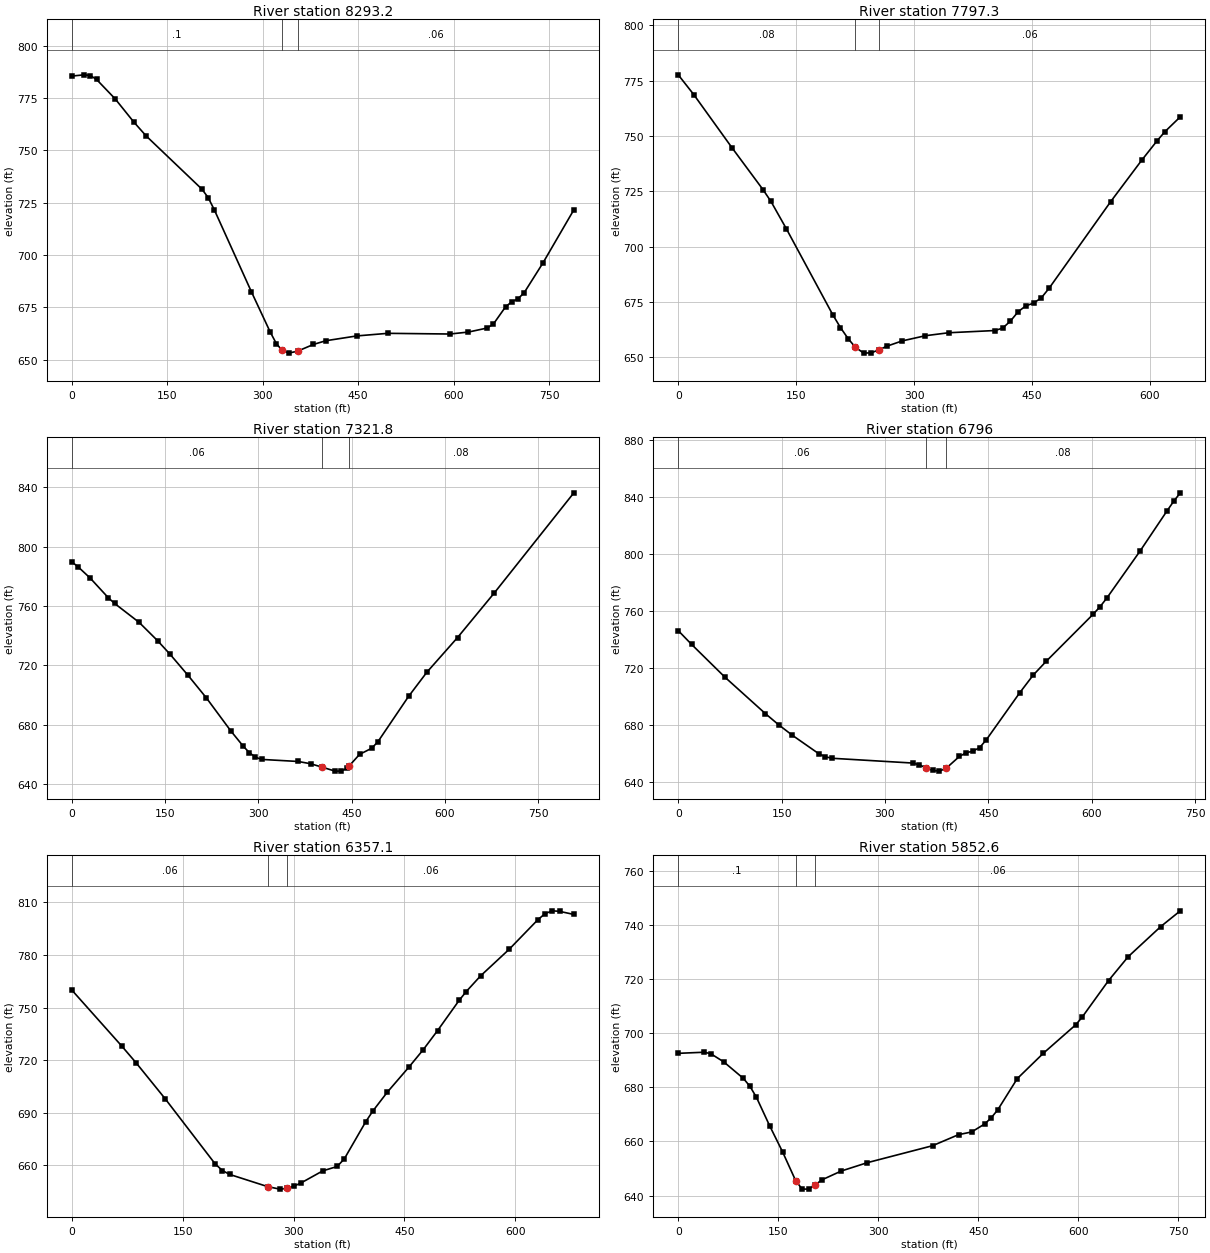
Type RM Length L Ch R = 1 ,8293.2  ,512.6,495.9,479.2
XS GIS Cut Line= 2
     1474621.719      237311.302     1475300.742      237712.893
#Sta/Elev= 30
       0  785.55    19.5  786.15    29.2  785.82      39  783.92    68.2  774.66
    97.4  763.62   116.9  756.95   204.5  731.53   214.3  727.51     224  721.64
   282.4   682.4   311.7  663.34   321.4  657.77   329.6654.8281   340.9  653.19
     355654.1537   379.8  657.35   399.3  659.12     448  661.41   496.7  662.65
   594.1  662.32   623.3  663.26   652.5  665.17   662.3     667   681.8  675.39
   691.5  677.74   701.2  679.14     711  682.13   740.2   696.2   788.9  721.66
#Mann= 3 , 0 , 0
       0      .1       0   329.6    .045       0     355     .06       0
Bank Sta=329.6,355
XS Rating Curve= 0 ,0
Exp/Cntr=0.3,0.1

Type RM Length L Ch R = 1 ,7797.3  ,452.8,475.5,494.4
XS GIS Cut Line= 2
     1474698.279      238015.298     1475323.141       237882.16
#Sta/Elev= 30
       0  777.62    19.7  768.72    68.8  744.46   108.1   725.6     118  720.37
   137.6  708.01   196.6  669.18   206.4  663.36   216.2  658.34   225.2654.5219
   235.9  651.79   245.6  651.93   255.6  653.29   265.4  654.91     285  657.32
   314.5  659.66     344     661     403  662.01   412.8   663.1   422.6  666.23
   432.5  670.49   442.3  673.18   452.1  674.38     462  676.77   471.8  681.06
   550.4  720.34   589.7  738.97   609.4  747.82   619.2  751.88   638.9  758.64
#Mann= 3 , 0 , 0
       0     .08       0   225.2    .045       0   255.6     .06       0
Bank Sta=225.2,255.6
XS Rating Curve= 0 ,0
Exp/Cntr=0.3,0.1

Type RM Length L Ch R = 1 ,7321.8  ,514.6,525.8,536.9
XS GIS Cut Line= 2
     1474679.981      238123.208     1475318.869      238616.264
#Sta/Elev= 30
       0  789.78     9.8  786.57    29.5  778.88      59  765.45    68.9   761.7
   108.3  748.93   137.8  736.63   157.5  727.65     187  713.12   216.5  697.89
   255.9  675.52   275.6  665.37   285.4  661.03   295.2  657.94   305.1  656.44
   364.1  655.04   383.8  653.52   402.9651.1557   423.2  648.53     433  648.54
   442.9  650.55   445.2651.7328   462.6  659.85   482.2     664   492.1   668.4
   541.3  698.94   570.8  715.32     620  738.68   679.1  768.79     807  836.39
#Mann= 3 , 0 , 0
       0     .06       0   402.9    .045       0   445.2     .08       0
Bank Sta=402.9,445.2
XS Rating Curve= 0 ,0
Exp/Cntr=0.3,0.1

Type RM Length L Ch R = 1 ,6796    ,436.4,439,440.9
XS GIS Cut Line= 2
     1474499.425      238394.042     1474777.203      239067.653
#Sta/Elev= 30
       0  746.02    19.4  736.34      68  713.26   126.3  687.89   145.7     680
   165.2  672.78     204  659.69   213.7  657.52   223.4  656.51     340  653.17
   349.8  651.94   359.5  649.88   369.2  647.98   378.9   647.5   388.6  649.41
     408  657.79   417.8  660.37   427.5   661.5   437.2  663.92   446.9  669.34
   495.5   702.4   514.9   714.7   534.3  724.66   602.3  757.59   612.1  762.77
   621.8  768.73   670.4  801.94   709.2  829.88   718.9  836.62   728.6  842.62
#Mann= 3 , 0 , 0
       0     .06       0   359.5    .045       0   388.6     .08       0
Bank Sta=359.5,388.6
XS Rating Curve= 0 ,0
Exp/Cntr=0.3,0.1

Type RM Length L Ch R = 1 ,6357.1  ,503.7,504.5,505.1
XS GIS Cut Line= 2
     1474145.258      238539.875     1474332.758      239192.653
#Sta/Elev= 30
       0  760.01    67.9  727.87    87.3   718.3   126.1  698.06     194  660.72
   203.8  656.96   213.4  654.76     265647.7733   281.4  646.34   291.2646.7239
   300.8  648.06   310.5  649.96   339.6  656.78     359  659.26   368.7  663.62
   397.8   684.9   407.5  691.04   426.9  701.71     456  715.96   475.4   725.9
   494.8  736.81   523.9  754.02   533.6  759.11     553  768.06   591.8  783.28
   630.7   800.2   640.4  803.62   650.1   805.2   659.8  804.91   679.2  803.13
#Mann= 3 , 0 , 0
       0     .06       0     265    .045       0   291.2     .06       0
Bank Sta=265,291.2
XS Rating Curve= 0 ,0
Exp/Cntr=0.3,0.1

Type RM Length L Ch R = 1 ,5852.6  ,550.2,595.8,641.1
XS GIS Cut Line= 2
     1473707.758      238769.042     1473895.258      239498.208
#Sta/Elev= 30
       0  692.59    39.1     693    48.9  692.44    68.4   689.4    97.8  683.29
   107.6  680.36   117.3  676.31   136.9  665.89   156.4  656.18     176  645.56
   185.8  642.37   195.6   642.4   205.3  643.91   215.1  645.76   244.4  649.06
   283.6  652.16   381.3  658.42   420.4  662.52     440  663.51   459.6  666.48
   469.3  668.74   479.1  671.68   508.4  683.24   547.6  692.64   596.4  703.21
   606.2  706.14   645.3  719.51   674.7  728.32   723.6  739.48   752.9  745.29
#Mann= 3 , 0 , 0
       0      .1       0     176    .045       0   205.3     .06       0
Bank Sta=176,205.3
XS Rating Curve= 0 ,0
Exp/Cntr=0.3,0.1

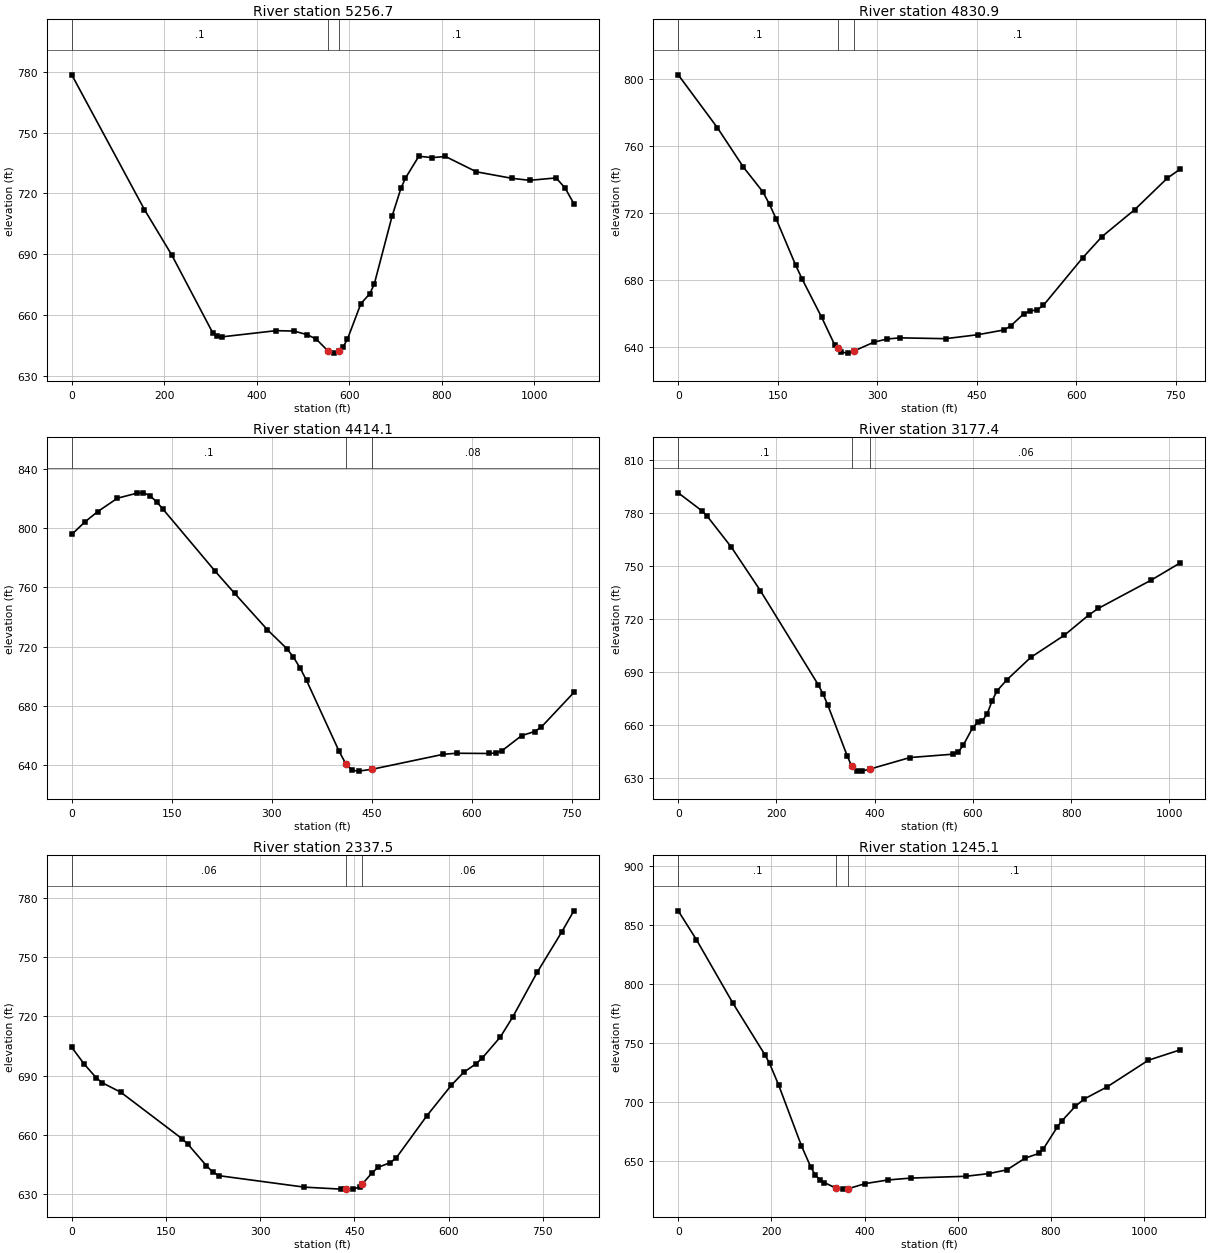
Type RM Length L Ch R = 1 ,5256.7  ,446.3,425.8,405.2
XS GIS Cut Line= 4
     1473853.592      238581.542      1473525.39       238863.08
       1473211.3      238811.435     1473131.369      239137.097
#Sta/Elev= 30
       0   778.5   157.2  711.97   216.2  689.59   304.6  651.29   314.5  649.48
   324.3  649.14   442.1  652.21   480.6  652.01   509.6   650.2   528.9  648.02
   553.3642.3966   567.4  641.12   578.8642.3078   586.7  644.11   596.4  648.07
   625.3  665.52   644.6  670.43   654.3   675.2   692.8  708.68   712.1  722.56
   721.8  727.53   750.7  738.31   779.5  737.62   808.2   738.2   875.3  730.62
   951.9  727.42   990.2  726.42  1047.7  727.61  1066.9  722.66    1086  714.91
#Mann= 3 , 0 , 0
       0      .1       0   553.3    .045       0   578.8      .1       0
Bank Sta=553.3,578.8
XS Rating Curve= 0 ,0
Exp/Cntr=0.3,0.1

Type RM Length L Ch R = 1 ,4830.9  ,436.5,416.8,397.1
XS GIS Cut Line= 2
     1473633.974      238269.042     1473071.474      238775.986
#Sta/Elev= 30
       0   802.5      59  771.01    98.3  747.48   127.8  732.67   137.7  725.26
   147.5   716.8     177  689.14   186.8  680.83   216.4  657.91     236  641.52
   240.7639.4462   245.7  637.24   255.7  636.64   265.7638.0275     295  643.14
   314.7  645.04   334.4  645.75   403.2  645.25   452.4  647.65   491.7  650.49
   501.5   652.9   521.2  660.12     531  661.81   540.9  662.35   550.7   665.1
   609.7  693.34   639.2  706.13   688.4  722.14   737.6  740.93   757.2  746.35
#Mann= 3 , 0 , 0
       0      .1       0   240.7    .045       0   265.7      .1       0
Bank Sta=240.7,265.7
XS Rating Curve= 0 ,0
Exp/Cntr=0.3,0.1

Type RM Length L Ch R = 1 ,4414.1  ,1236.3,1236.7,1235.1
XS GIS Cut Line= 2
      1473038.22      237909.783     1473057.852      238663.023
#Sta/Elev= 30
       0  795.65    19.6  804.05    39.1  811.11    68.5  820.08    97.9  823.49
   107.6  823.71   117.4  821.78   127.2  817.66     137  812.64   215.3   770.8
   244.6  755.84   293.6  731.39   322.9   718.6   332.7  712.93   342.5  705.72
   352.3  697.27   401.2  649.46   411.7640.6393   420.8   636.6   430.6  636.07
   451.3637.3739   557.8  647.43   577.4  648.13   626.3  647.96   636.1   648.3
   645.8  649.87   675.2  660.03   694.8  662.77   704.6  665.74   753.5  689.09
#Mann= 3 , 0 , 0
       0      .1       0   411.7    .045       0   451.3     .08       0
Bank Sta=411.7,451.3
XS Rating Curve= 0 ,0
Exp/Cntr=0.3,0.1

Type RM Length L Ch R = 1 ,3177.4  ,833.6,840,843.3
XS GIS Cut Line= 2
     1471839.703      237824.597     1471895.258      238845.431
#Sta/Elev= 30
       0  791.56    49.2  781.16      59  778.31   108.1  760.81   167.1  736.22
   285.1  682.86   294.9  677.62   304.7  671.22   344.1  642.57   352.8636.9594
   363.7  634.08   373.6  633.94   391.4635.2039   471.8  641.63   560.3  643.56
   570.2  644.76     580  648.49   599.6  658.56   609.5  661.59   619.3  662.45
   629.1  666.37     639  673.69   648.8  679.29   668.5  685.48   717.6  698.32
   786.4  710.94   835.6   722.3   855.2  726.09   963.4  742.18  1022.3  751.92
#Mann= 3 , 0 , 0
       0      .1       0   352.8    .045       0   391.4     .06       0
Bank Sta=352.8,391.4
XS Rating Curve= 0 ,0
Exp/Cntr=0.3,0.1

Type RM Length L Ch R = 1 ,2337.5  ,1095.3,1092.4,1086.9
XS GIS Cut Line= 2
     1471245.828      238171.965       1471131.9      238963.135
#Sta/Elev= 30
       0  704.26    19.5  695.92      39  688.84    48.7  686.34      78  681.59
   175.5   658.1   185.2  655.18   214.4  644.42   224.2  641.31     234  639.41
   370.4   633.6   428.9   632.6   437.2   632.6   448.4  632.62   458.2  633.77
   462.2635.0608   477.6  640.68   487.4  643.58   506.9  645.98   516.6  648.41
   565.4  669.72   604.4  685.17   623.9  691.62   643.4  695.93   653.1  698.73
   682.4  709.54   701.8  719.49   740.8  742.12   779.8  762.46   799.3  773.28
#Mann= 3 , 0 , 0
       0     .06       0   437.2    .045       0   462.2     .06       0
Bank Sta=437.2,462.2
XS Rating Curve= 0 ,0
Exp/Cntr=0.3,0.1

Type RM Length L Ch R = 1 ,1245.1  ,728.6,711.9,694.3
XS GIS Cut Line= 2
     1470534.147      237491.264     1470589.703      238567.653
#Sta/Elev= 30
       0  862.05    39.2  837.49   117.6  783.63   186.2  739.98     196  732.79
   215.6  714.36   264.6  662.81   284.2   645.2     294  638.23   303.8  634.24
   313.6  631.79   339.6626.8406   352.7  626.21   364.9626.5751   401.7  630.92
   450.7     634   499.7  635.58   617.3  637.09   666.3  639.35   705.5  642.53
   744.7  652.48   774.1  656.43   783.9  660.38   813.3  678.56   823.1   683.8
   852.5  696.44   872.1  702.72     921  712.94  1009.2  735.44  1077.8  744.27
#Mann= 3 , 0 , 0
       0      .1       0   339.6    .045       0   364.9      .1       0
Bank Sta=339.6,364.9
XS Rating Curve= 0 ,0
Exp/Cntr=0.3,0.1