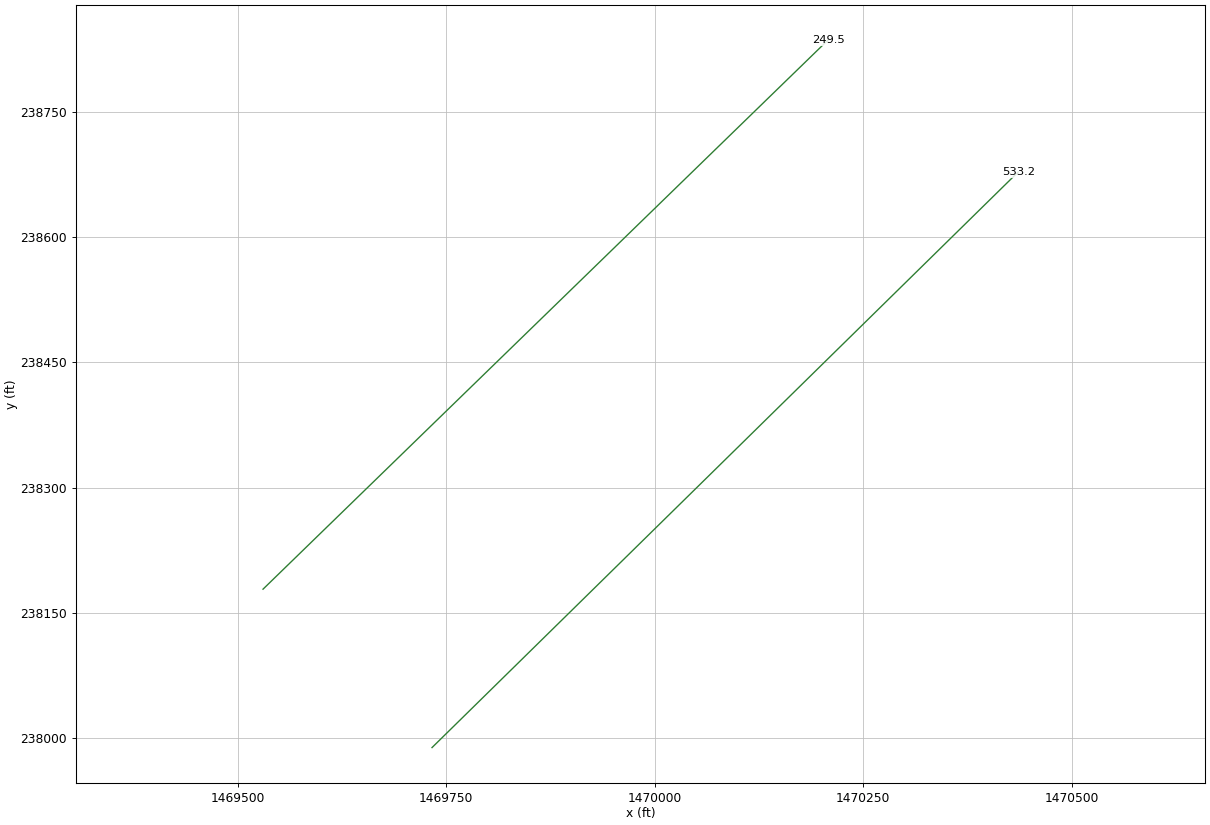
HEC-RAS study GLLSPRN.prj: GLLSPRN

--- GLLSPRN.g01 (geometry) --- (continued)

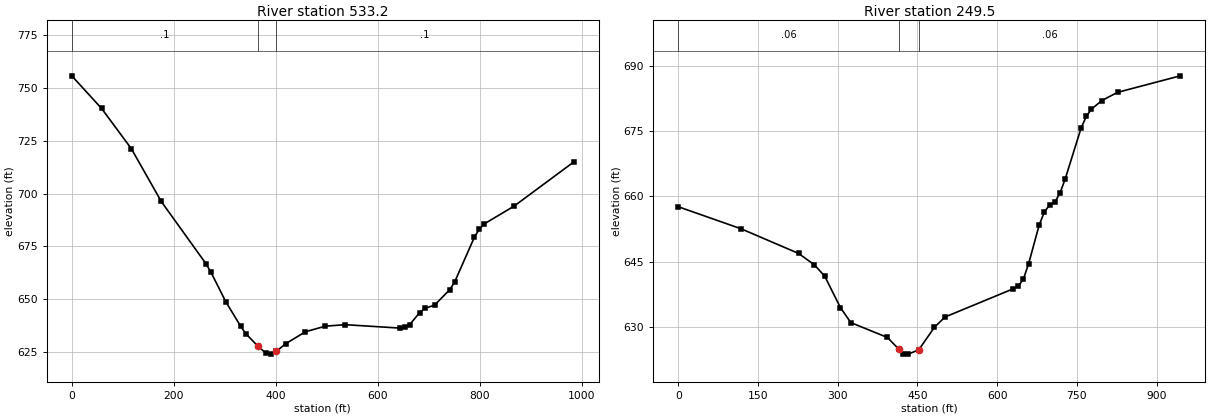
Type RM Length L Ch R = 1 ,533.2   ,282,283.7,285.2
XS GIS Cut Line= 2
     1469733.111      237988.413      1470435.67      238678.313
#Sta/Elev= 30
       0  755.85    58.5  740.37     117  721.23   175.5  696.26   263.2  666.72
     273  662.68   302.2  648.65   331.5  636.96   341.2   633.6   364.3627.7884
   380.2  624.38     390  623.85   401.2625.1538   419.2  628.74   458.2  634.45
   497.2   637.1   536.2  637.82   643.4   636.2   653.2  636.48   662.9  637.89
   682.4  643.57   692.2   645.5   711.7  647.11   740.9  654.32   750.7  657.93
   789.7  679.34   799.4  683.17   809.2  685.65   867.7  694.08   984.7  715.03
#Mann= 3 , 0 , 0
       0      .1       0   364.3    .045       0   401.2      .1       0
Bank Sta=364.3,401.2
XS Rating Curve= 0 ,0
Exp/Cntr=0.3,0.1

Type RM Length L Ch R = 1 ,249.5   ,245,249.5,248.3
XS GIS Cut Line= 2
     1469530.572      238178.294     1470207.813      238836.547
#Sta/Elev= 30
       0  657.63     118  652.56   226.3  646.88   255.8  644.29   275.5  641.65
     305  634.43   324.6  630.96   393.5  627.53   414.5624.8913     423  623.72
   432.9   623.7   452.5  624.71     482  629.89   501.7  632.24   629.6  638.71
   639.5  639.31   649.3  640.98   659.1  644.52   678.8  653.36   688.6  656.39
   698.5  658.04   708.3  658.65   718.2  660.82     728  664.07   757.5  675.64
   767.4   678.4   777.2  680.09   796.9  682.08   826.4  683.96   944.4  687.76
#Mann= 3 , 0 , 0
       0     .06       0   414.5    .045       0   452.5     .06       0
Bank Sta=414.5,452.5
XS Rating Curve= 0 ,0
Exp/Cntr=0.3,0.1

Chan Stop Cuts=-1
Use User Specified Reach Order=0
Composite Channel Slope=5